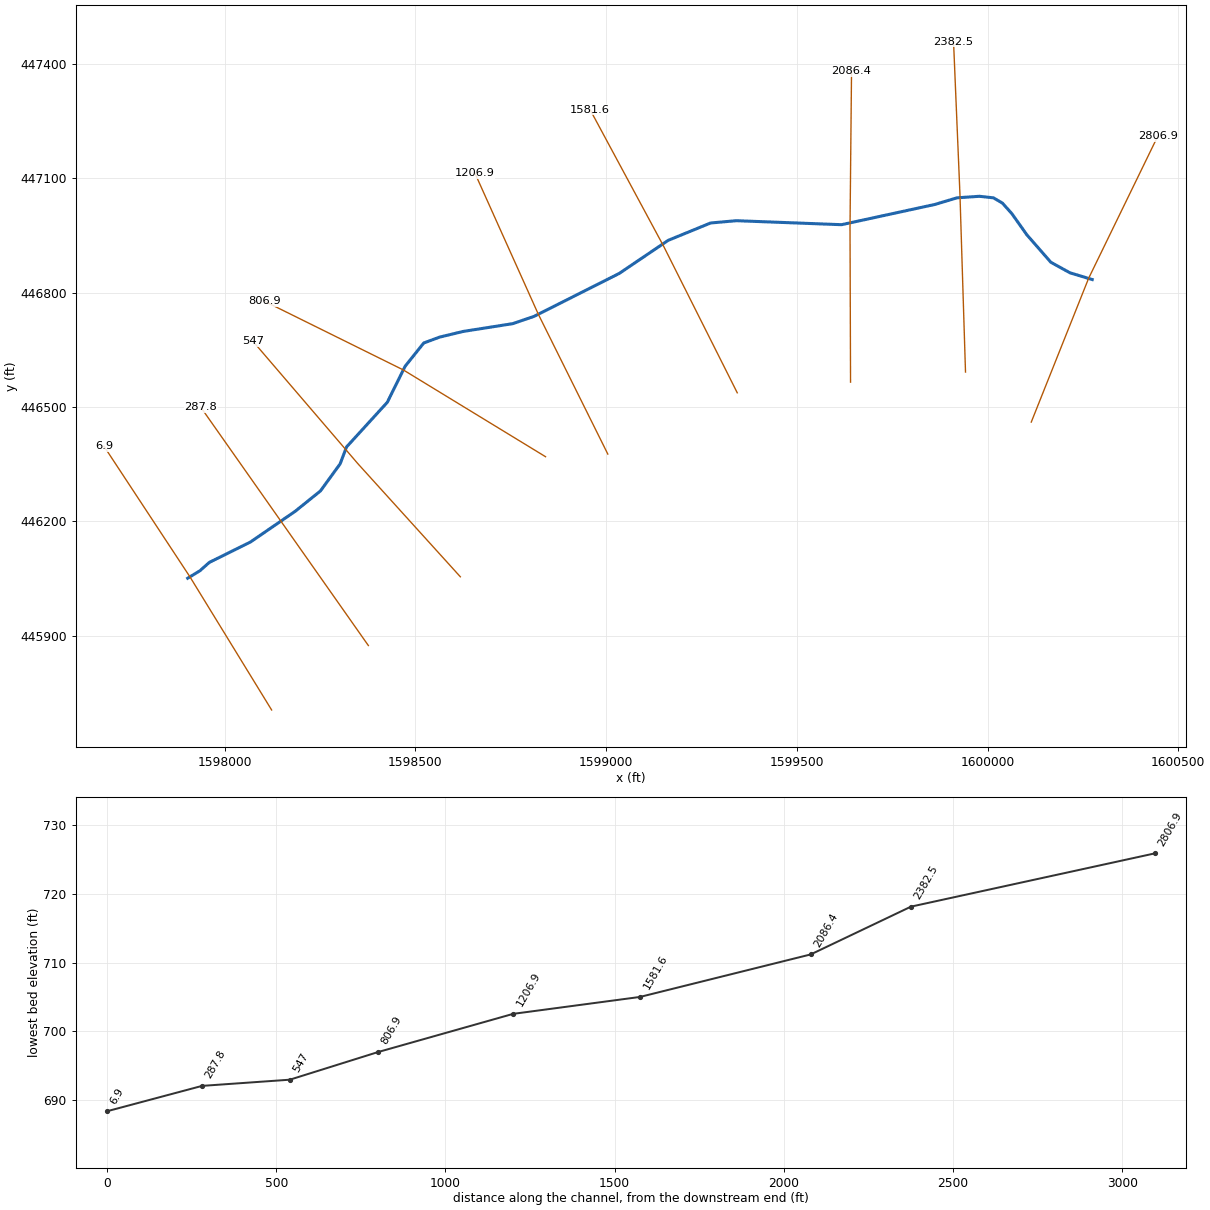
--- WOLFPENBR.prj (project) ---

Proj Title=WOLFPENBR
Current Plan=p01
Default Exp/Contr=0,0
English Units
Geom File=g01
Flow File=f01
Plan File=p01
BEGIN DESCRIPTION:
END DESCRIPTION:
DSS Export Rating Curves= 0
DSS Export Rating Curve Sorted= 0
DSS Export Volume Flow Curves= 0
DXF OffsetX= 0
DXF OffsetY= 0
DXF ScaleX= 0
DXF ScaleY= 0

--- WOLFPENBR.p01 (plan) ---

Plan Title=Floodplain
Program Version=4.00
Geom File=g01
Flow File=f01
K Sum by GR=0
Std Step Tol=0.01
Critical Tol=0.01
Num of Std Step Trials=20
Max Error Tol=0.3
Flow Tol Ratio=0.001
Split Flow NTrial=30
Split Flow Tol=0.02
Split Flow Ratio=0.02
Log Output Level=0
Friction Slope Method=1
Unsteady Friction Slope Method=2
Unsteady Bridges Friction Slope Method=1
Global Log Level=0
CheckData=False
Run HTab=0
Run UNet=0
Run PostProcess=0
UNET Theta=0
UNET Theta Warmup=0
UNET ZTol=0
UNET ZSATol=0
UNET MxIter=0
UNET MaxInSteps=0
UNET DtIC=0
UNET DtMin=0
UNET MaxCRTS=0
UNET WFStab=0
UNET SFStab=0
UNET WFX=0
UNET SFX=0
UNET DSS MLevel=0
UNET DZMax Abort=0
UNET Convert EG Bridges=0
UNET Use Existing IB Tables=0
UNET Froude Limit=0
UNET Froude Power=0
Write IC File=0
Echo Input=False
Echo Output=False
Write Detailed=0

--- WOLFPENBR.f01 (steady flow) ---

Flow Title=NFF Regression Equation
Program Version=4.00
Number of Profiles= 1
Profile Names=P100yr
River Rch & RM=WOLFPENBR,Main            ,2806.9
     358
River Rch & RM=WOLFPENBR,Main            ,2382.5
     363
River Rch & RM=WOLFPENBR,Main            ,2086.4
     427
River Rch & RM=WOLFPENBR,Main            ,287.8
     464
Boundary for River Rch & Prof#=WOLFPENBR,Main            , 1
Up Type= 0
Dn Type= 3
Dn Slope=0.010685
DSS Import GetInterval= 0
DSS Import GetPeak= 0
DSS Import FillOption= 0

--- WOLFPENBR.g01 (geometry) ---

Geom Title=USGS 10m DEM
Program Version=4.00

River Reach=WOLFPENBR       ,Main
Reach XY= 30
     1600274.362      446833.968     1600215.783      446851.771
     1600165.818      446879.338     1600102.644        446951.7
     1600063.592      447006.833     1600038.897        447034.4
      1600015.35      447048.183     1599978.595      447052.203
     1599920.016      447048.183     1599861.839      447030.773
      1599617.35      446977.749     1599341.327      446988.229
      1599273.96      446982.204     1599162.696      446936.616
     1599034.584      446849.991      1598811.13      446737.341
     1598755.285      446718.336     1598625.392      446697.918
     1598564.019      446683.142     1598522.094      446667.668
     1598473.175      446606.381     1598426.592      446512.216
     1598319.675       446395.02     1598302.925      446350.746
     1598251.268       446279.73     1598184.925      446226.318
      1598067.68      446145.835     1597960.012      446092.509
     1597935.968      446071.049     1597903.371      446051.051

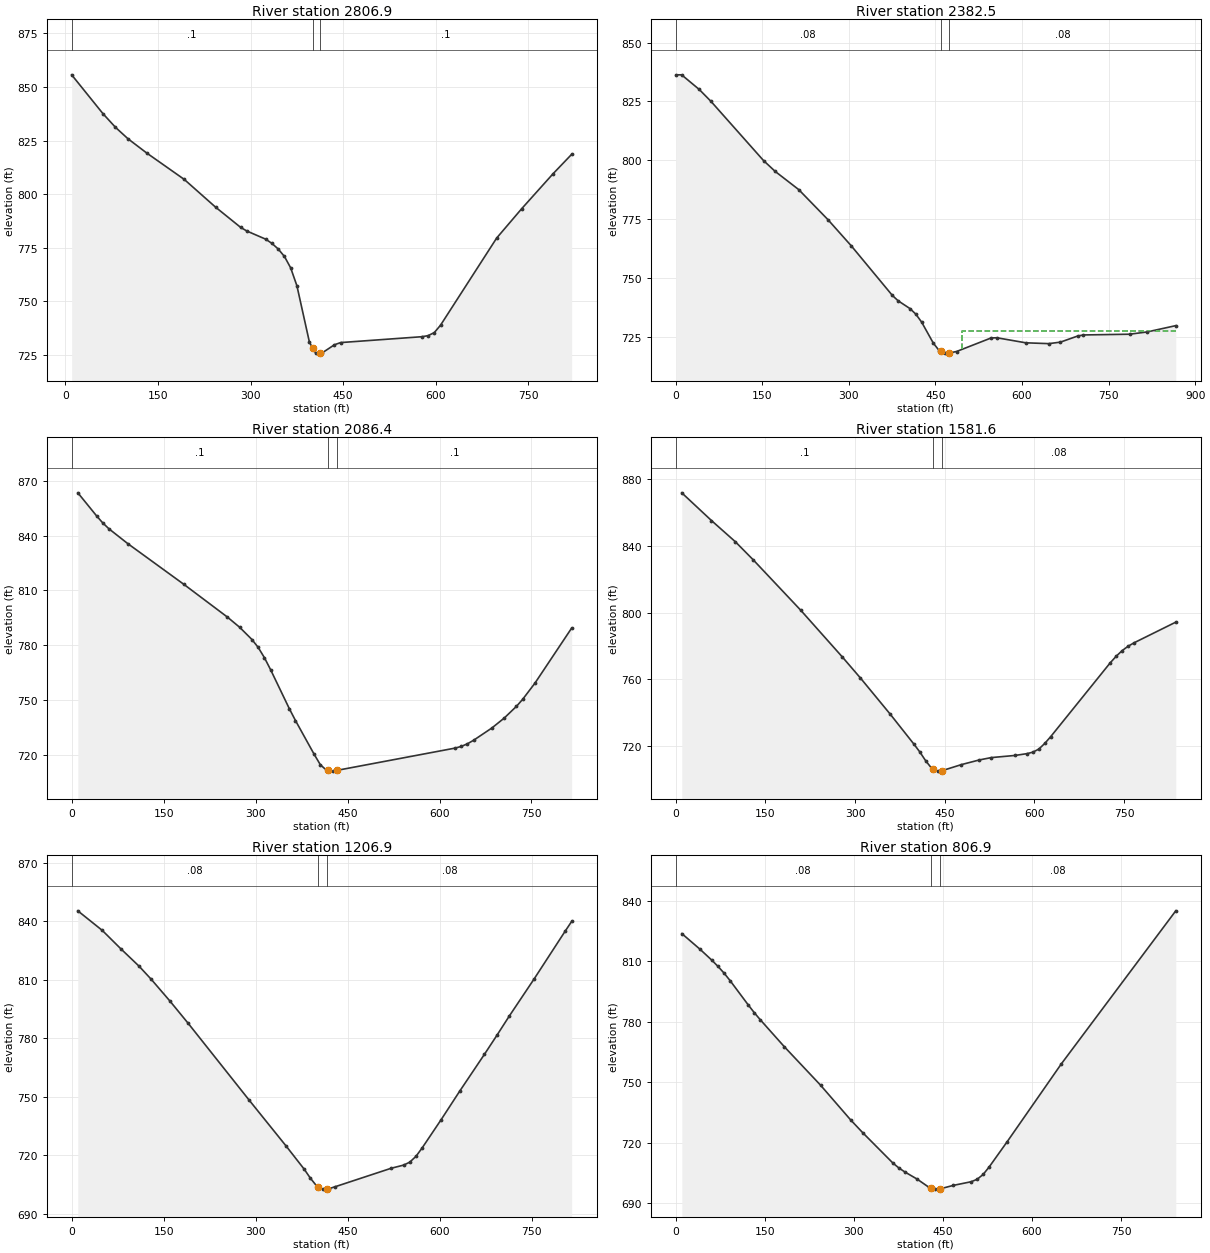
Type RM Length L Ch R = 1 ,2806.9  ,712,720.5,730.6
XS GIS Cut Line= 3
     1600114.562      446460.339     1600264.837      446837.015
     1600446.228      447209.867
#Sta/Elev= 30
    10.1  855.62    60.8  837.52    81.1  831.15   101.4  825.81   131.8  819.16
   192.6  806.86   243.3  793.94   283.9  784.52     294  782.81   324.4  779.03
   334.6  777.05   344.7  774.46   354.9  770.95     365  765.62   375.1  757.27
   395.4  730.95  400.55  728.36   405.5  725.91     413  725.95   415.7  725.97
   435.9  729.81     446  730.83   577.5  733.56   587.6  734.05   597.7  735.49
   607.8  738.93   698.8  779.57   739.3  793.23   789.8  809.42   820.2  818.55
#Mann= 3 , 0 , 0
    10.1      .1       0  400.55    .045       0     413      .1       0
Bank Sta=400.55,413
XS Rating Curve= 0 ,0
Exp/Cntr=0.3,0.1

Type RM Length L Ch R = 1 ,2382.5  ,297,296.1,295
XS GIS Cut Line= 3
       1599942.2       446591.55     1599927.623      447057.851
     1599910.839      447457.372
#Sta/Elev= 30
       0  836.32    10.1  836.32    40.6  830.11    60.9  825.06   152.1   799.9
   172.4  795.28     213  787.59   263.7  774.82   304.3  763.65   375.3  742.65
   385.4  740.36   405.7  737.09   415.8  734.75     426  731.33   446.2  722.43
   456.4  719.23     459  718.95   466.5  718.16     474  718.22   486.5  718.85
   546.5  724.61   556.5  724.68   606.5  722.54   646.5  722.19   666.5  722.83
   696.5  725.43   706.5  725.88   786.4  726.19   816.4  727.14   866.4  729.83
#Mann= 3 , 0 , 0
       0     .08       0     459    .045       0     474     .08       0
#XS Ineff= 2 , 0
                          495.89          727.39
Permanent Ineff=
       F       F
Bank Sta=459,474
XS Rating Curve= 0 ,0
Exp/Cntr=0.3,0.1

Type RM Length L Ch R = 1 ,2086.4  ,493.9,504.8,516.2
XS GIS Cut Line= 3
     1599640.863      446565.008      1599639.46      446970.724
     1599643.474      447380.447
#Sta/Elev= 30
    10.1  863.36    40.6  850.78    50.7  846.91    60.9  843.67    91.3  835.65
   182.6  813.43   253.6  795.54   273.9  789.89   294.1  783.15   304.3  778.81
   314.4  773.24   324.6  766.58     355  745.38   365.1  738.84   395.6  720.38
   405.7  714.66   415.7   711.7   418.2  711.58   425.7  711.21   433.2  711.66
   625.6  723.81   635.6  724.73   645.6  726.16   655.6  728.08   685.5  734.81
   705.5   740.2   725.5  746.63   735.5  750.41   755.5  759.23   815.5  789.39
#Mann= 3 , 0 , 0
       0      .1       0   418.2    .045       0   433.2      .1       0
Bank Sta=418.2,433.2
XS Rating Curve= 0 ,0
Exp/Cntr=0.3,0.1

Type RM Length L Ch R = 1 ,1581.6  ,375,374.7,373.1
XS GIS Cut Line= 3
     1599343.913      446537.089     1599151.736      446919.712
     1598958.151      447279.297
#Sta/Elev= 30
      10   871.8    59.7  855.18    99.6   842.5   129.4   831.7   209.1  801.42
   278.8  773.37   308.7  760.93   358.5  739.28   398.3  721.27   408.3  716.51
   418.2  711.18   428.2  706.68   430.6  706.28   438.1  705.02   445.6   705.3
     478  708.94   507.9  711.72   527.8  713.13   567.6  714.42   587.5  715.49
   597.5  716.38   607.5  718.25   617.4  721.63   627.4  725.72     727  769.96
     737   773.9   746.9  777.24   756.9  779.87   766.8  781.92   836.6   794.3
#Mann= 3 , 0 , 0
       0      .1       0   430.6    .045       0   445.6     .08       0
Bank Sta=430.6,445.6
XS Rating Curve= 0 ,0
Exp/Cntr=0.3,0.1

Type RM Length L Ch R = 1 ,1206.9  ,387.2,400,415.6
XS GIS Cut Line= 3
     1599004.588      446376.474     1598822.487      446742.984
     1598656.105      447113.223
#Sta/Elev= 30
      10  845.34    49.9   835.3    79.9  825.94   109.8  816.97   129.8  810.19
   159.7  799.25   189.7  787.73   289.5  748.18   349.4  724.78   379.3  712.73
   389.3  708.15   399.3  704.24   401.8  703.82   409.3  702.56   416.8  702.71
   419.4  702.77   429.6  703.79   520.9  713.26   541.2  714.88   551.3   716.4
   561.5  719.42   571.6  723.76   602.1  738.04   632.5  752.73   673.1  771.76
   693.4  781.49   713.7  791.43   754.3  810.52     805  835.07   815.2  839.87
#Mann= 3 , 0 , 0
       0     .08       0   401.8    .045       0   416.8     .08       0
Bank Sta=401.8,416.8
XS Rating Curve= 0 ,0
Exp/Cntr=0.3,0.1

Type RM Length L Ch R = 1 ,806.9   ,267.7,259.9,250.2
XS GIS Cut Line= 3
     1598841.382      446369.579     1598468.566      446597.065
     1598105.163      446776.841
#Sta/Elev= 30
    10.2  823.62    40.6  815.93    60.9   810.4    71.1  807.36    81.3  804.05
    91.4  800.35   121.9  788.33     132  784.51   142.2  780.97   182.8  767.57
   243.8  748.52   294.5   731.3   314.9  724.95   365.6  709.94   375.8  707.47
     386  705.47   406.3     702   426.6  697.86   429.2  697.64   436.7  696.99
   444.2  697.18   446.9  697.25   467.1  698.82   497.6  700.66   507.7  701.88
   517.8  704.29     528  708.03   558.4  720.58   649.6  759.14   842.2  834.92
#Mann= 3 , 0 , 0
       0     .08       0   429.2    .045       0   444.2     .08       0
Bank Sta=429.2,444.2
XS Rating Curve= 0 ,0
Exp/Cntr=0.3,0.1

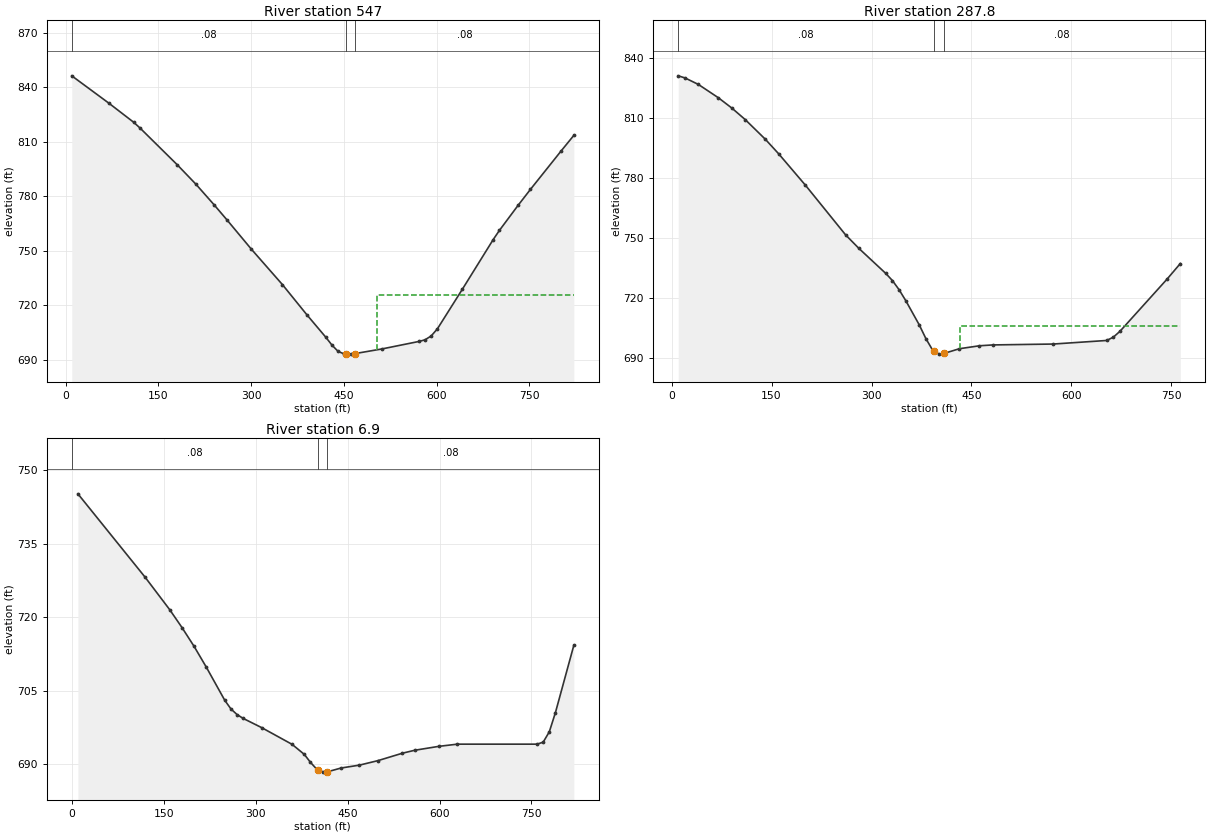
Type RM Length L Ch R = 1 ,547     ,260.6,259.2,257.8
XS GIS Cut Line= 3
     1598618.035      446054.863     1598349.003      446351.813
     1598074.895      446671.605
#Sta/Elev= 30
      10  846.36    70.1  831.26   110.2  820.74   120.2  817.65   180.3  797.43
   210.4  786.76   240.4  775.19   260.5  767.15   300.5  750.79   350.6  731.32
   390.7  714.45   420.8  702.29   430.8  697.93   440.8  694.45   450.8  693.06
   453.4  693.04   460.9  692.98   468.4   693.3     511   695.8   571.2  699.95
   581.2  700.86   591.2  702.99   601.3  706.95   641.4  728.62   691.5  756.12
   701.5  761.15   731.6  774.92   751.7  783.77   801.8  805.15   821.9  813.54
#Mann= 3 , 0 , 0
      10     .08       0   453.4    .045       0   468.4     .08       0
#XS Ineff= 2 , 0
                          504.23          725.51
Permanent Ineff=
       F       F
Bank Sta=453.4,468.4
XS Rating Curve= 0 ,0
Exp/Cntr=0.3,0.1

Type RM Length L Ch R = 1 ,287.8   ,282.3,280.8,280.1
XS GIS Cut Line= 2
     1598376.922      445874.662     1597937.842      446499.019
#Sta/Elev= 30
      10  830.89    20.1  829.85    40.2   826.6    70.3  819.93    90.4  814.82
   110.5  809.06   140.6  799.28   160.7  791.99   200.9  776.31   261.1  751.57
   281.2  744.77   321.4  732.33   331.4  728.76   341.5  724.14   351.5  718.69
   371.6  706.68   381.6   699.8   391.7  694.06   394.2  693.56   401.7  692.08
   409.2  692.47   431.9  694.78     462  696.25   482.1  696.67   572.5  697.11
   652.8  698.89   662.9  700.56   672.9  703.51   743.2  729.41   763.3  737.26
#Mann= 3 , 0 , 0
      10     .08       0   394.2    .045       0   409.2     .08       0
#XS Ineff= 2 , 0
                          433.43          705.88
Permanent Ineff=
       F       F
Bank Sta=394.2,409.2
XS Rating Curve= 0 ,0
Exp/Cntr=0.3,0.1

Type RM Length L Ch R = 1 ,6.9     ,6.9,6.9,6.2
XS GIS Cut Line= 3
     1598123.407      445705.672     1597909.285      446054.679
     1597684.034      446396.962
#Sta/Elev= 30
      10   745.2   119.8  728.16   159.8  721.55   179.8  717.91   199.7  714.04
   219.7  709.78   249.7  703.04   259.7  701.29   269.6  700.15   279.6  699.36
   309.6  697.49   359.5  694.06   379.5     692   389.5  690.38   399.5  689.02
     402  688.86   409.5  688.39     417  688.45   439.4  689.23   469.4  689.82
   499.4  690.73   539.4  692.25   559.4  692.85   599.3  693.66   629.3   694.1
   759.2   694.1   769.2  694.51   779.2  696.63   789.2  700.56   819.2  714.29
#Mann= 3 , 0 , 0
       0     .08       0     402    .045       0     417     .08       0
Bank Sta=402,417
XS Rating Curve= 0 ,0
Exp/Cntr=0.3,0.1

Chan Stop Cuts=-1
Use User Specified Reach Order=0